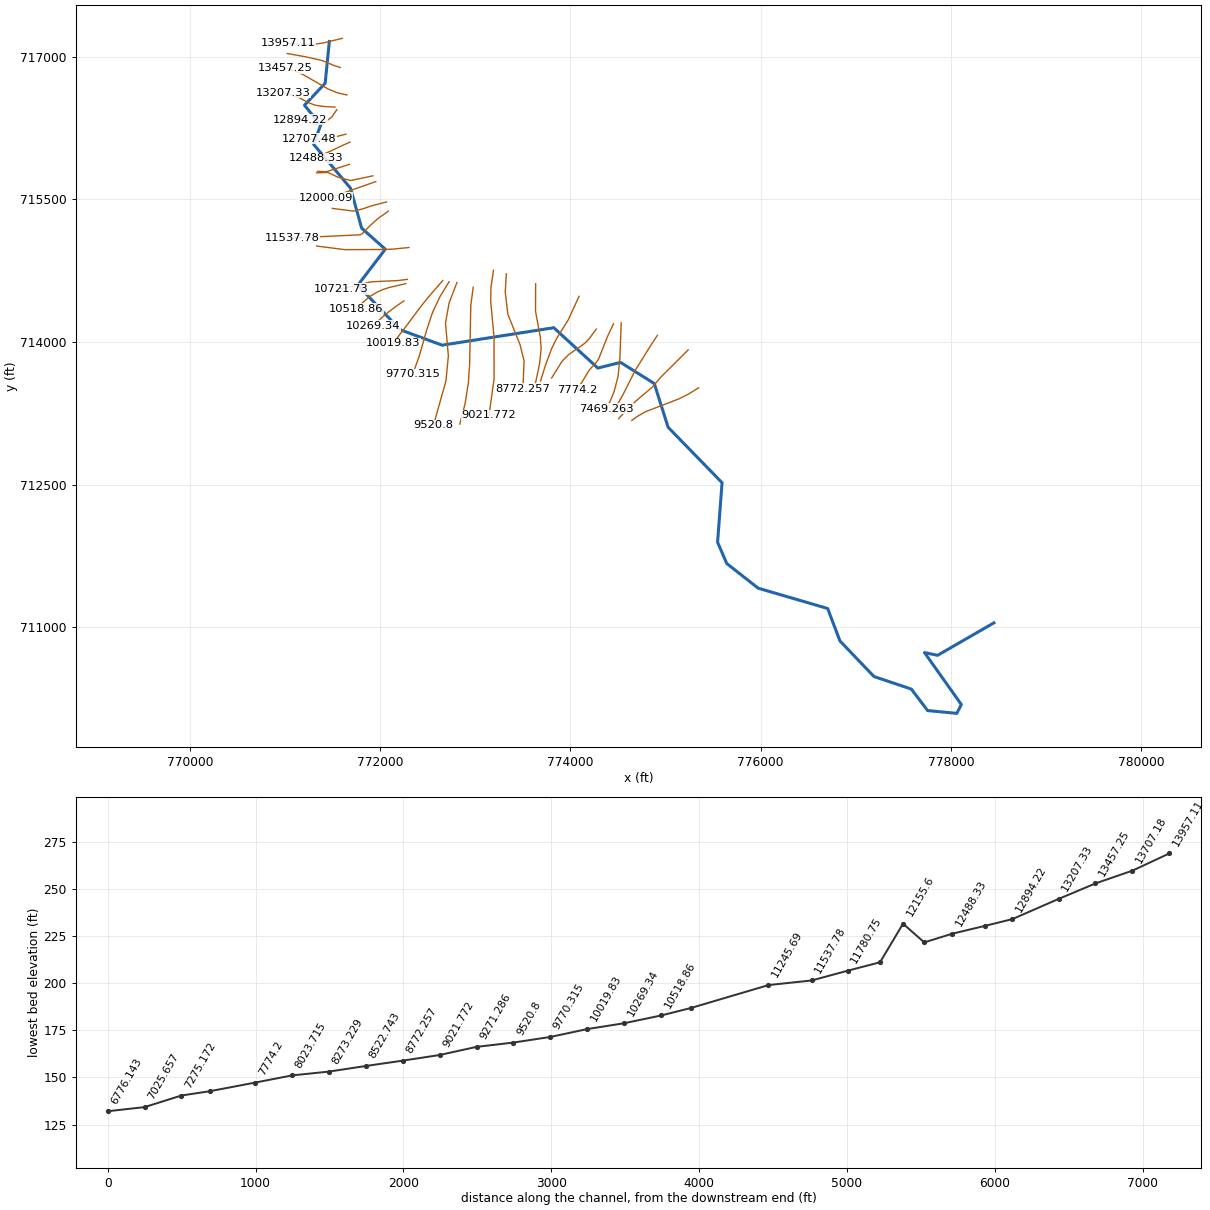
--- 6602_ras.prj (project) ---

Proj Title=6602
Current Plan=p01
Default Exp/Contr=0.3,0.1
English Units
Geom File=g01
Flow File=f01
Plan File=p01
Y Axis Title=Elevation
X Axis Title(PF)=Main Channel Distance
X Axis Title(XS)=Station
BEGIN DESCRIPTION:
RFD model 6602 exported to HEC-RAS
END DESCRIPTION:

--- 6602_ras.p01 (plan) ---

Plan Title=Plan 01
Program Version=4.10
Short Identifier=Plan 01
Geom File=g01
Flow File=f01
Subcritical Flow
Calc Critical at every XS
Secant Critical Depth

--- 6602_ras.f01 (steady flow) ---

Flow Title=Flow 01
Program Version=5.01
Number of Profiles= 6
Profile Names=10yr,25yr,50yr,100yr,100plus,500yr
River Rch & RM=6602,38,13957.11
  716.18 1210.59 1696.07  2165.5 3161.64 4721.46
River Rch & RM=6602,38,13707.18
  718.29 1214.51 1701.89 2173.33 3173.05 4737.93
River Rch & RM=6602,38,13457.25
   748.7  1270.2 1783.91 2282.59 3332.58 4963.55
River Rch & RM=6602,38,13207.33
  752.01 1276.35 1793.04 2294.83 3350.45 4989.11
River Rch & RM=6602,38,12894.22
  754.58 1281.14 1800.18 2304.43 3364.46 5009.26
River Rch & RM=6602,38,12707.48
  755.24 1282.39 1802.05 2306.96 3368.16 5014.62
River Rch & RM=6602,38,12488.33
  798.41 1362.07 1919.99 2464.77 3598.56 5340.52
River Rch & RM=6602,38,12299.11
  831.06 1422.25 2009.04 2583.89 3772.48 5584.39
River Rch & RM=6602,38, 12155.6
  834.13 1428.03 2017.69 2595.59 3789.56  5608.8
River Rch & RM=6602,38,12000.09
  836.23 1431.98 2023.61 2603.58 3801.23 5625.48
River Rch & RM=6602,38,11780.75
  838.17 1435.63 2029.07 2610.96    3812 5640.86
River Rch & RM=6602,38,11537.78
  854.45 1466.06 2074.45 2672.08 3901.24 5767.11
River Rch & RM=6602,38,11245.69
  855.42 1467.87 2077.17 2675.75  3906.6 5774.73
River Rch & RM=6602,38,10721.73
 1270.26 2216.19  3171.4 4124.89 6022.34 8553.08
River Rch & RM=6602,38,10518.86
 1271.68 2218.88 3175.45  4130.4 6030.38 8563.95
River Rch & RM=6602,38,10269.34
 1273.66 2222.65 3181.12  4138.1 6041.63 8579.17
River Rch & RM=6602,38,10019.83
 1276.79 2228.56 3190.03  4150.2 6059.29 8603.05
River Rch & RM=6602,38,9770.315
 1286.04 2246.07 3216.37 4185.95 6111.49 8673.48
River Rch & RM=6602,38,  9520.8
 1288.02 2249.82 3222.03 4193.64 6122.71 8688.62
River Rch & RM=6602,38,9271.286
 1293.59 2260.41 3238.03 4215.43 6154.53 8731.82
River Rch & RM=6602,38,9021.772
 1312.09 2296.12 3292.38 4289.91 6263.27 8881.28
River Rch & RM=6602,38,8772.257
 1336.67 2342.48 3362.06 4384.41 6401.23 9065.94
River Rch & RM=6602,38,8522.743
 1344.15 2356.61  3383.3 4413.23 6443.32 9122.22
River Rch & RM=6602,38,8273.229
 1425.34 2505.19 3602.66 4706.17 6871.01 9670.47
River Rch & RM=6602,38,8023.715
 1427.11 2508.55 3607.74 4713.08  6881.1 9683.94
River Rch & RM=6602,38,  7774.2
 1443.99 2540.53 3655.92 4778.59 6976.74 9811.03
River Rch & RM=6602,38,7469.263
  1447.9 2548.05 3667.37 4794.27 6999.63 9841.93
River Rch & RM=6602,38,7275.172
 1456.58 2564.62 3692.45 4828.49  7049.6 9908.75
River Rch & RM=6602,38,7025.657
 1459.62 2570.44 3701.27 4840.54 7067.19 9932.35
River Rch & RM=6602,38,6776.143
 1461.15 2573.41  3705.8 4846.76 7076.28 9944.66
River Rch & RM=6602,38,6526.629
 1485.28 2620.46 3777.91 4946.18 7221.4210142.77
River Rch & RM=6602,38,6277.114
 1501.47  2651.5 3825.02  5010.6 7315.47 10268.6
River Rch & RM=6602,38,  6027.6
  1504.8 2657.99 3834.97 5024.33 7335.5310295.92
River Rch & RM=6602,38,5661.968
    1883 3334.62 4820.29 6323.91 9232.9212580.07
River Rch & RM=6602,38,5408.753
 1884.62 3337.79 4825.18 6330.68 9242.7912593.15
River Rch & RM=6602,38,5162.005
 1885.32 3339.16 4827.28 6333.58 9247.0212598.75
River Rch & RM=6602,38,4915.258
 1889.77    3348 4840.98 6352.64 9274.86 12636.1
River Rch & RM=6602,38,4421.763
 1896.08 3360.64 4860.65 6380.08 9314.9112690.18
Boundary for River Rch & Prof#=6602,38,1
Up Type= 0
Dn Type= 2
Boundary for River Rch & Prof#=6602,38,2
Up Type= 0
Dn Type= 2
Boundary for River Rch & Prof#=6602,38,2
Up Type= 0
Dn Type= 2
Boundary for River Rch & Prof#=6602,38,2
Up Type= 0
Dn Type= 2
Boundary for River Rch & Prof#=6602,38,2
Up Type= 0
Dn Type= 2
Boundary for River Rch & Prof#=6602,38,2
Up Type= 0
Dn Type= 2

--- 6602_ras.g01 (geometry) ---

Geom Title=6602
Program Version=4.10

River Reach=6602,38
Reach XY= 30
771465.886580261717158.455076451771421.835179122716719.280363701
771204.414626062716488.787309382771374.709324065716279.421624759
771300.703297497716077.346843307771688.297503979715616.929323041
771805.459031613715196.311959109772054.124582619714974.667381846
771765.014739515714595.920886642 772209.99386111714128.217529324
772651.363970372713965.862500961773825.258808017714149.438837132
774288.407362192713725.239390647774527.182484657713785.216127096
774881.994706183 713562.26527814775027.412664834713102.958873115
775594.527007493712519.914273855775547.370640638711894.370534595
775643.848439873 711670.40792099775974.203255358711411.081193739
776704.689920127711197.724964779776833.652348341710856.768966484
777191.289070547710482.582375899777583.929072558 710350.67988718
777755.645590874710124.797592753778062.467480692710095.092863193
 778109.93315801710187.934115942777722.532184753710734.430514308
  777859.5911316710705.179375671778451.856218073711046.240953471

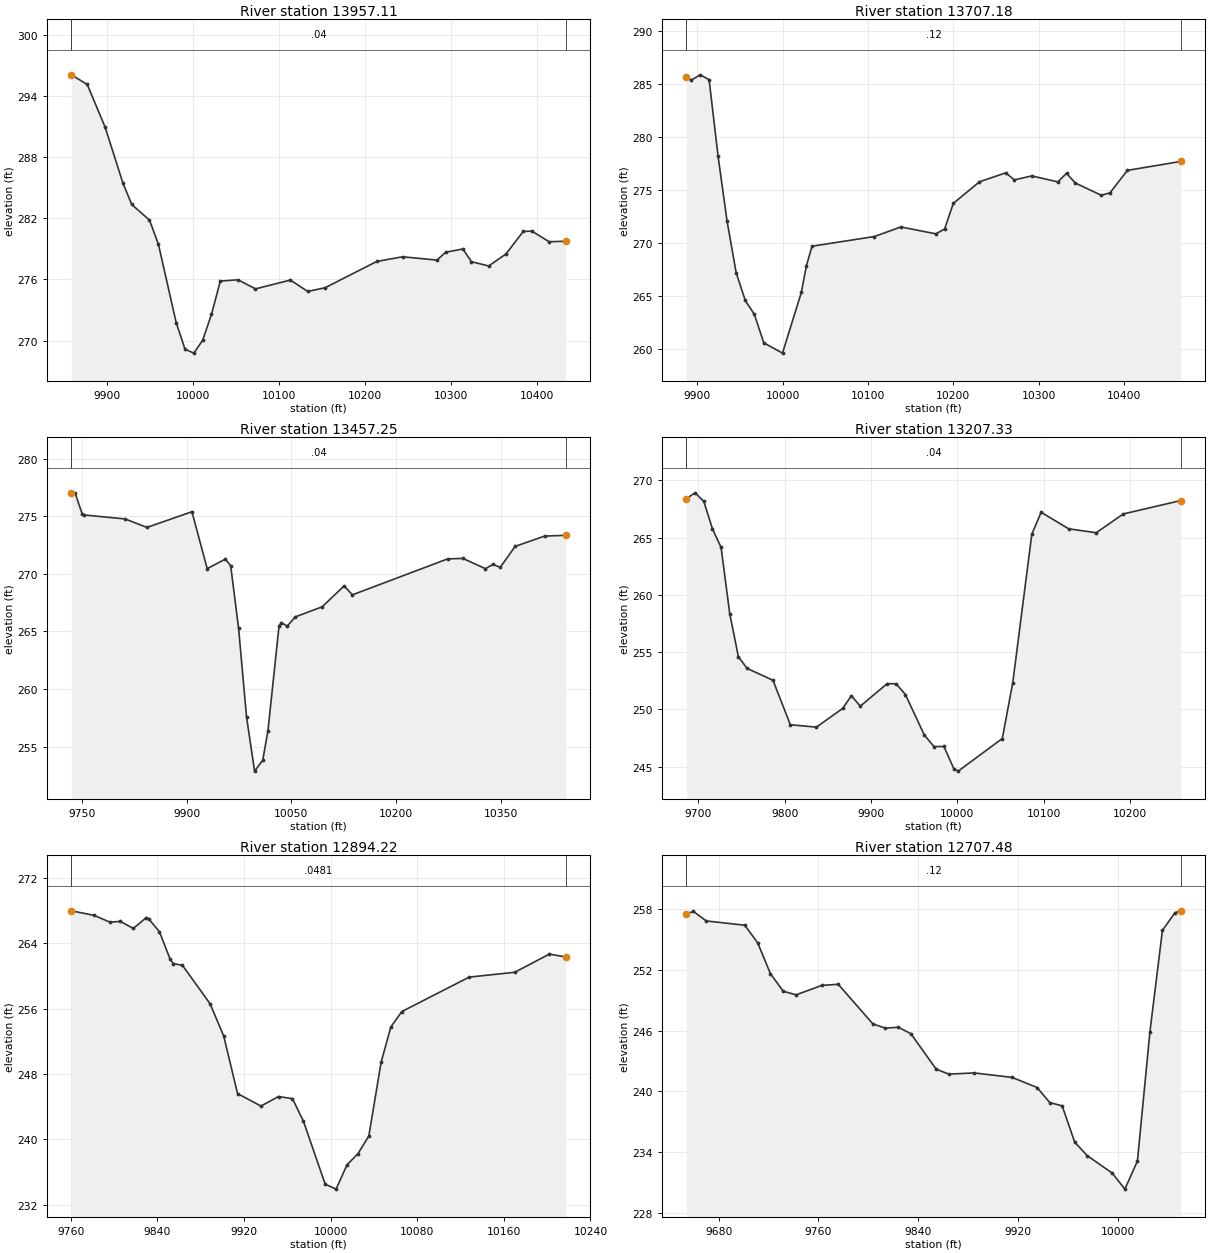
Type RM Length L Ch R = 1 ,13957.11,249.925700,249.925700,249.925700
XS GIS Cut Line= 6
771603.007396808717191.654955303771407.201245443717144.336187574
771327.591613168717132.214161427771262.763445732717128.815368335
771167.729809387  717130.6159497 771035.78258808717139.823577229
#Sta/Elev= 30
9858.854296.05889877.275295.1125 9897.94290.94929918.605285.47619928.937283.3442
9949.601281.81199959.934279.44599980.598 271.7589990.869269.149810001.11268.7661
10011.36270.0277 10021.6272.565810031.85275.828810052.34275.958610072.74275.0682
10113.27275.931110133.43274.8159 10153.5275.174610213.58277.754610243.58278.2141
10283.59277.887810293.59278.661210313.62278.977210323.64277.732410343.68 277.313
10363.73278.493910383.77280.695710393.79280.733410413.85279.690710433.14279.7357
#Mann= 3 , 0 , 0
9858.854    0.04       09858.854    0.04       010433.14    0.04       0
#XS Ineff= 2 , 0
       0                               0
Bank Sta=9858.854,10433.14
Exp/Cntr=0.3,0.1

Type RM Length L Ch R = 1 ,13707.18,249.925600,249.925600,249.925600
XS GIS Cut Line= 6
771580.791312603716885.448739363771506.419957151 716908.98019083
771443.741028991716937.777217016771376.373285408716961.929945235
771214.535901314716997.866576003771023.458302537717032.426231744
#Sta/Elev= 30
9887.427285.64369893.411285.38149903.743285.87159914.074285.41229924.511278.2282
9935.138272.05559945.766267.19949956.393264.5965 9967.07263.27899978.041260.6009
9999.995259.629210022.07265.362410027.92  267.8510034.49269.710310107.52270.6218
10138.48271.527310179.51270.877310189.73271.332710199.94273.750510230.58275.7876
10261.23276.627410271.44275.967310291.79276.337910322.31275.775310332.48276.5869
10342.65275.674410373.17274.513610383.35274.742910403.69276.8618 10466.1277.7023
#Mann= 3 , 0 , 0
9887.427    0.12       09887.427    0.12       0 10466.1    0.12       0
#XS Ineff= 2 , 0
       0                               0
Bank Sta=9887.427,10466.1
Exp/Cntr=0.3,0.1

Type RM Length L Ch R = 1 ,13457.25,249.925600,249.925600,249.925600
XS GIS Cut Line= 6
771650.240002346 716596.62330224 771556.12994401716617.470746486
 771455.18722776716657.717850179771186.396161425716812.477420071
771124.468269627716839.687425092771005.834978526716878.851551024
#Sta/Elev= 30
9734.986276.97939740.285277.02379750.397275.19199753.696275.09899811.907274.7567
9843.216274.02059907.692275.38219929.518  270.449955.545271.27049963.172 270.694
9974.538265.25319985.905257.55779997.422252.863510009.09253.808910016.56256.3701
10032.43265.453710035.96265.7525 10044.1265.448710055.77266.255710094.17267.1275
10125.78268.948310137.45268.166210273.87271.286610295.71 271.33110328.18270.4375
10338.79270.8115 10349.4270.557510370.61272.373210412.82273.268910443.13273.3349
#Mann= 3 , 0 , 0
9734.986    0.04       09734.986    0.04       010443.13    0.04       0
#XS Ineff= 2 , 0
       09966.467                       0
Bank Sta=9734.986,10443.13
Exp/Cntr=0.3,0.1

Type RM Length L Ch R = 1 ,13207.33,313.110300,313.110300,313.110300
XS GIS Cut Line= 6
771525.188017249716469.188447803771416.286258012716474.397693351
771318.772232354716488.585706368771248.776612997716514.024948955
771141.388629675716570.896481782770980.650709927716620.490482926
#Sta/Elev= 30
9686.279268.39699696.473268.90019706.479 268.1479716.485265.76619726.491 264.138
9736.497258.37379746.512  254.61 9756.53253.58749786.585252.54789806.662248.6729
9836.823248.4587 9867.25250.08949877.427251.20869887.603250.28739918.751252.2529
9929.188252.24019939.901 251.3079961.759247.77849972.948246.76799984.564246.7724
 9996.18244.8013   10001244.6237 10052.1247.468410064.24252.351610086.25 265.285
10097.02267.203810128.94 265.76110160.85265.418810192.15267.057110258.64268.2243
#Mann= 3 , 0 , 0
9686.279    0.04       09686.279    0.04       010258.64    0.04       0
#XS Ineff= 2 , 0
       0 9889.52                       0
Bank Sta=9686.279,10258.64
Exp/Cntr=0.3,0.1

Type RM Length L Ch R = 1 ,12894.22,186.740900,186.740900,186.740900
XS GIS Cut Line= 6
771544.863526523716442.493265018771493.938017249716366.757892236
771405.396350533716297.313447803771323.799128324716286.896781147
771266.507461667716299.049558908771160.604683906716335.507892236
#Sta/Elev= 30
9760.555267.98539781.636267.42729796.153266.59839805.737266.68569817.787265.8321
9829.838267.16769831.996266.99959841.888265.4236 9851.82262.05699854.669261.5355
9863.179261.30929888.597256.62689901.306252.64519914.015245.61799935.688244.0911
9951.891245.25849964.746244.99239974.827242.25479994.989234.527410005.07233.9222
10015.15236.900110025.23238.251410035.31240.431810046.61 249.428 10055.6253.7637
10065.82255.659510127.92259.869110170.22260.468310201.95262.685610217.17262.3492
#Mann= 3 , 0 , 0
9760.555  0.0481       09760.555  0.0481       010217.17  0.0481       0
#XS Ineff= 2 , 0
       09965.983                       0
Bank Sta=9760.555,10217.17
Exp/Cntr=0.3,0.1

Type RM Length L Ch R = 1 ,12707.48,219.148400,219.148400,219.148400
XS GIS Cut Line= 6
771640.473875445716184.153880195771513.289703652716152.838114082
771425.570882699716136.304070731771355.491231323716126.080899347
771332.018989202716126.154249246771250.374159207716134.555341519
#Sta/Elev= 30
9654.014257.56849659.699257.80639670.018256.86599700.897256.4431 9711.19254.7135
9721.483251.64749731.776249.90389742.069249.55059762.655250.48339775.876250.5979
9803.613246.68279813.789246.24749823.966246.34679834.142  245.719854.494242.1898
 9864.67241.70089884.948241.81959915.265241.37999935.477 240.3779945.578238.8867
9955.578238.55899965.578234.97719975.634233.63619995.796231.899610005.88230.3154
10015.96233.099510026.01245.918710036.03255.937910046.05257.674310050.68257.8684
#Mann= 3 , 0 , 0
9654.014    0.12       09654.014    0.12       010050.68    0.12       0
#XS Ineff= 2 , 0
       0                               0
Bank Sta=9654.014,10050.68
Exp/Cntr=0.3,0.1

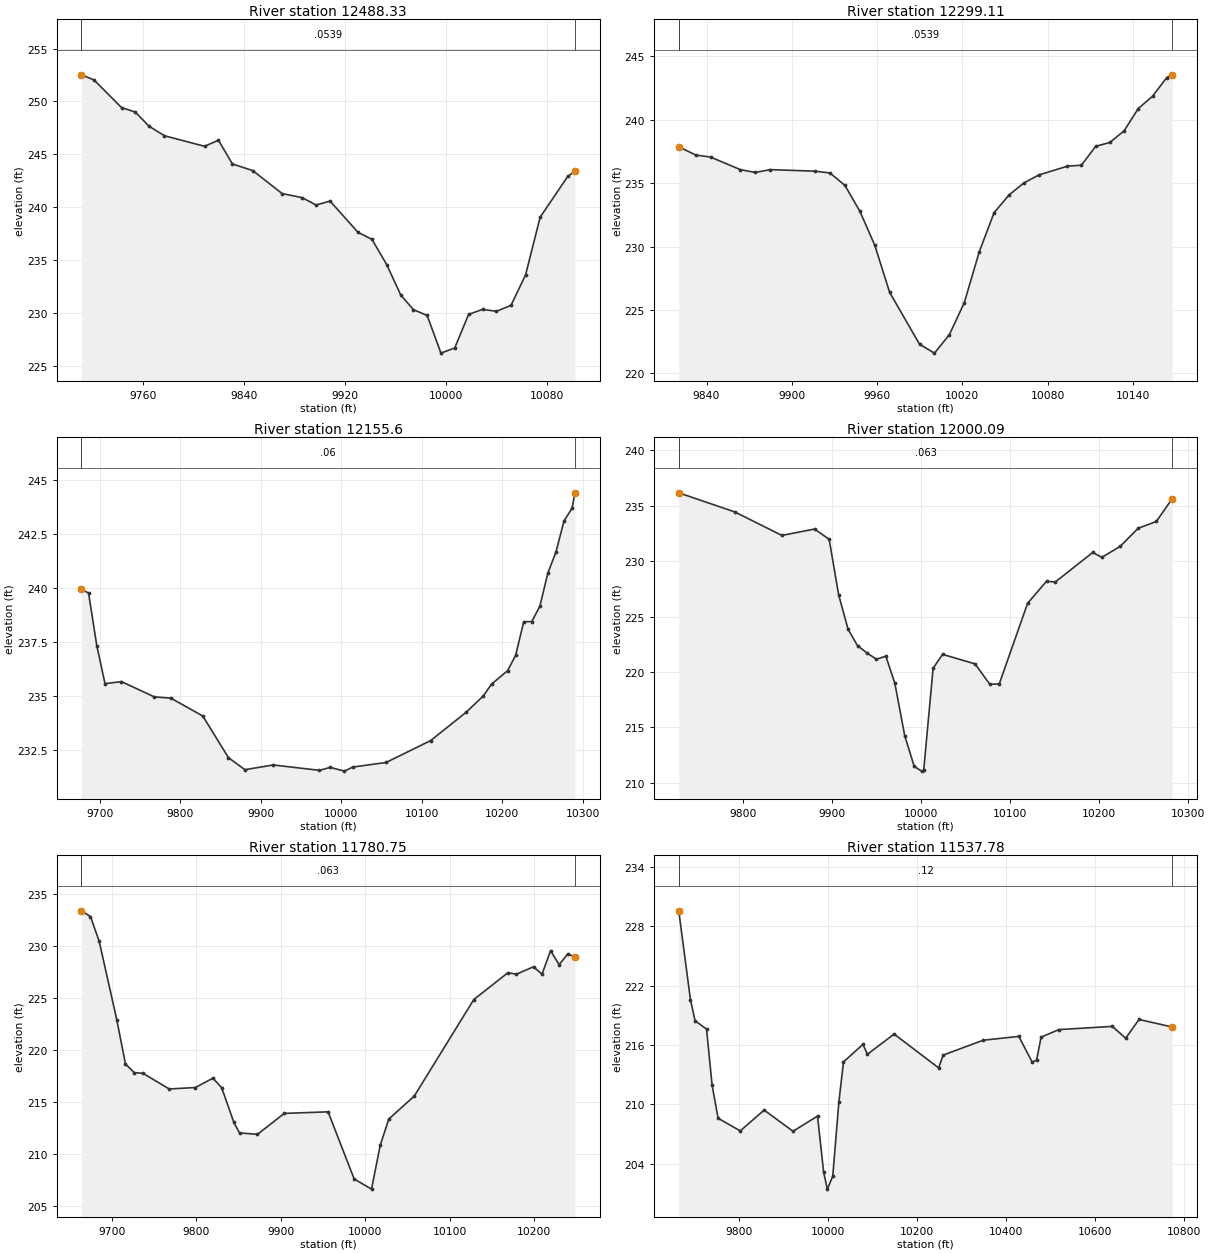
Type RM Length L Ch R = 1 ,12488.33,189.223700,189.223700,189.223700
XS GIS Cut Line= 6
 771684.16833687716101.095188863771623.703742245 716074.98731679
771464.413890322715999.476447453771417.648086611715979.056609194
771384.284244318715963.470269537771331.548942052715931.956088337
#Sta/Elev= 30
 9711.02252.51929721.007252.03339742.792249.42499753.684249.00019764.577247.6648
9776.849246.75939808.646245.76359819.713 246.332 9830.78 244.0919846.887243.4646
9870.232241.29039886.113240.9067 9897.18240.20719908.247240.5846 9930.38237.6232
9941.447236.96589953.162234.57679964.315231.69689974.359230.31729985.277229.7636
9996.195226.203810007.12226.692510018.15229.864510029.19230.338910040.23230.1606
10051.76230.717610063.32233.591910074.89 239.05610096.77242.908610102.46243.4047
#Mann= 3 , 0 , 0
 9711.02  0.0539       0 9711.02  0.0539       010102.46  0.0539       0
#XS Ineff= 2 , 0
       0                               0
Bank Sta=9711.02,10102.46
Exp/Cntr=0.3,0.1

Type RM Length L Ch R = 1 ,12299.11,143.504100,143.504100,143.504100
XS GIS Cut Line= 3
771676.344637036715866.766567156771436.508168817715790.048690677
771341.169448495715792.283191919
#Sta/Elev= 30
9820.449237.8593 9832.36237.21089842.859237.04949863.857236.05529874.356235.8359
9884.856236.05999916.353235.93749926.852235.79459937.351234.8183 9947.85232.7845
 9958.35230.10379968.849226.38469989.847222.307310000.35221.603310010.85223.0571
10021.34225.575710031.84229.576110042.34232.673610052.84234.064910063.34235.0167
10073.77235.636210093.77236.326110103.77236.408510113.78237.892810123.78238.2005
10133.78239.115610143.78240.873910153.79 241.83910163.79243.312710167.62243.5272
#Mann= 3 , 0 , 0
9820.449  0.0539       09820.449  0.0539       010167.62  0.0539       0
#XS Ineff= 2 , 0
       0                               0
Bank Sta=9820.449,10167.62
Exp/Cntr=0.3,0.1

Type RM Length L Ch R = 1 , 12155.6,155.511800,155.511800,155.511800
XS GIS Cut Line= 5
771923.629442781715746.103499293771690.496478319715696.944471627
771554.936735451715732.696491748771450.660010099715781.855519414
771331.486609757715777.386516899
#Sta/Elev= 30
9677.232 239.9559686.051239.76999696.271237.33789706.491235.57079726.931235.6658
 9767.81234.9564 9788.25234.90029827.981 234.0699859.789232.14059880.229231.5797
9915.491231.79919972.885231.54889986.293231.686410003.91231.512910014.25231.7014
10055.62231.913510110.89232.927310155.12234.242710176.63235.008310186.64235.5477
10206.65236.173110216.66236.890510226.67238.442910236.68238.452210246.68239.1606
10256.69240.7059 10266.7241.6781 10276.7243.117510286.71243.713810290.23244.4246
#Mann= 3 , 0 , 0
9677.232    0.06       09677.232    0.06       010290.23    0.06       0
#XS Ineff= 2 , 0
       09920.468                       0
Bank Sta=9677.232,10290.23
Exp/Cntr=0.3,0.1

Type RM Length L Ch R = 1 ,12000.09,219.339900,219.339900,219.339900
XS GIS Cut Line= 3
771954.167626619 715685.77196537771543.019395411715540.529383659
771427.570163757715517.439537346
#Sta/Elev= 30
9728.263236.15349791.014234.43589844.042232.31279880.691232.88859897.071231.9633
9907.676226.97239918.282223.84659928.887222.37319939.493221.71799950.099221.1524
9960.704221.42339970.758218.98849981.916214.23959992.521211.487310000.78211.0623
10003.13211.122510013.73 220.33810024.34 221.58910060.82220.731310077.37218.8907
10087.97218.928710119.79226.1969   10141228.179210150.89228.117310192.89230.7782
10203.08230.336210223.48231.316310243.88 232.95710264.27233.569610282.05235.6215
#Mann= 3 , 0 , 0
9728.263   0.063       09728.263   0.063       010282.05   0.063       0
#XS Ineff= 2 , 0
       09950.819                       0
Bank Sta=9728.263,10282.05
Exp/Cntr=0.3,0.1

Type RM Length L Ch R = 1 ,11780.75,242.966600,242.966600,242.966600
XS GIS Cut Line= 6
772065.317981309715472.093228309771892.035283857 715425.39292687
771840.906692528715406.627245022771800.965549969715394.946924059
771718.946967178715375.439072443771496.475869476715403.981094604
#Sta/Elev= 30
9663.948233.38769674.634232.8385 9684.99230.43529705.704222.91859716.061218.6366
9726.418 217.8099736.774217.74099767.845216.23369798.915216.37429819.629 217.277
9829.986216.34689844.404213.00649851.076212.00079872.348211.8661 9904.05213.8816
9955.939214.03179986.811207.567510007.35206.589210017.61210.794810027.79213.3355
10057.98215.551110128.43224.842210168.83227.429110178.93227.284210199.13228.0005
10209.23227.289910219.33229.552310229.43228.197910239.53229.219410248.13228.9804
#Mann= 3 , 0 , 0
9663.948   0.063       09663.948   0.063       010248.13   0.063       0
#XS Ineff= 2 , 0
       09927.226                       0
Bank Sta=9663.948,10248.13
Exp/Cntr=0.3,0.1

Type RM Length L Ch R = 1 ,11537.78,292.091700,292.091700,292.091700
XS GIS Cut Line= 6
772086.855318934 715375.31979357771976.821049412715297.108123889
771897.140127952715225.788672407771809.969450641715136.451914383
771787.644614458715126.219697803771070.527885906715092.102943942
#Sta/Elev= 30
9664.718229.5728 9690.98 220.6039701.365218.45239727.198217.61089739.671 211.946
9753.094208.59539803.023207.31529856.682 209.421  9921.6207.27769976.679208.8079
9990.449203.13589998.854201.423210010.92202.718310024.68210.223610035.08214.2864
10078.84216.067110088.85215.061710148.95217.1072 10249.1213.683710259.12214.9811
10349.22216.483210429.29216.873210459.32214.266210469.33214.490710479.34216.7958
10519.38217.558110639.49217.884210669.52 216.68410699.55218.5849 10774.1217.8226
#Mann= 3 , 0 , 0
9664.718    0.12       09664.718    0.12       0 10774.1    0.12       0
#XS Ineff= 2 , 0
       09821.604                       0
Bank Sta=9664.718,10774.1
Exp/Cntr=0.3,0.1

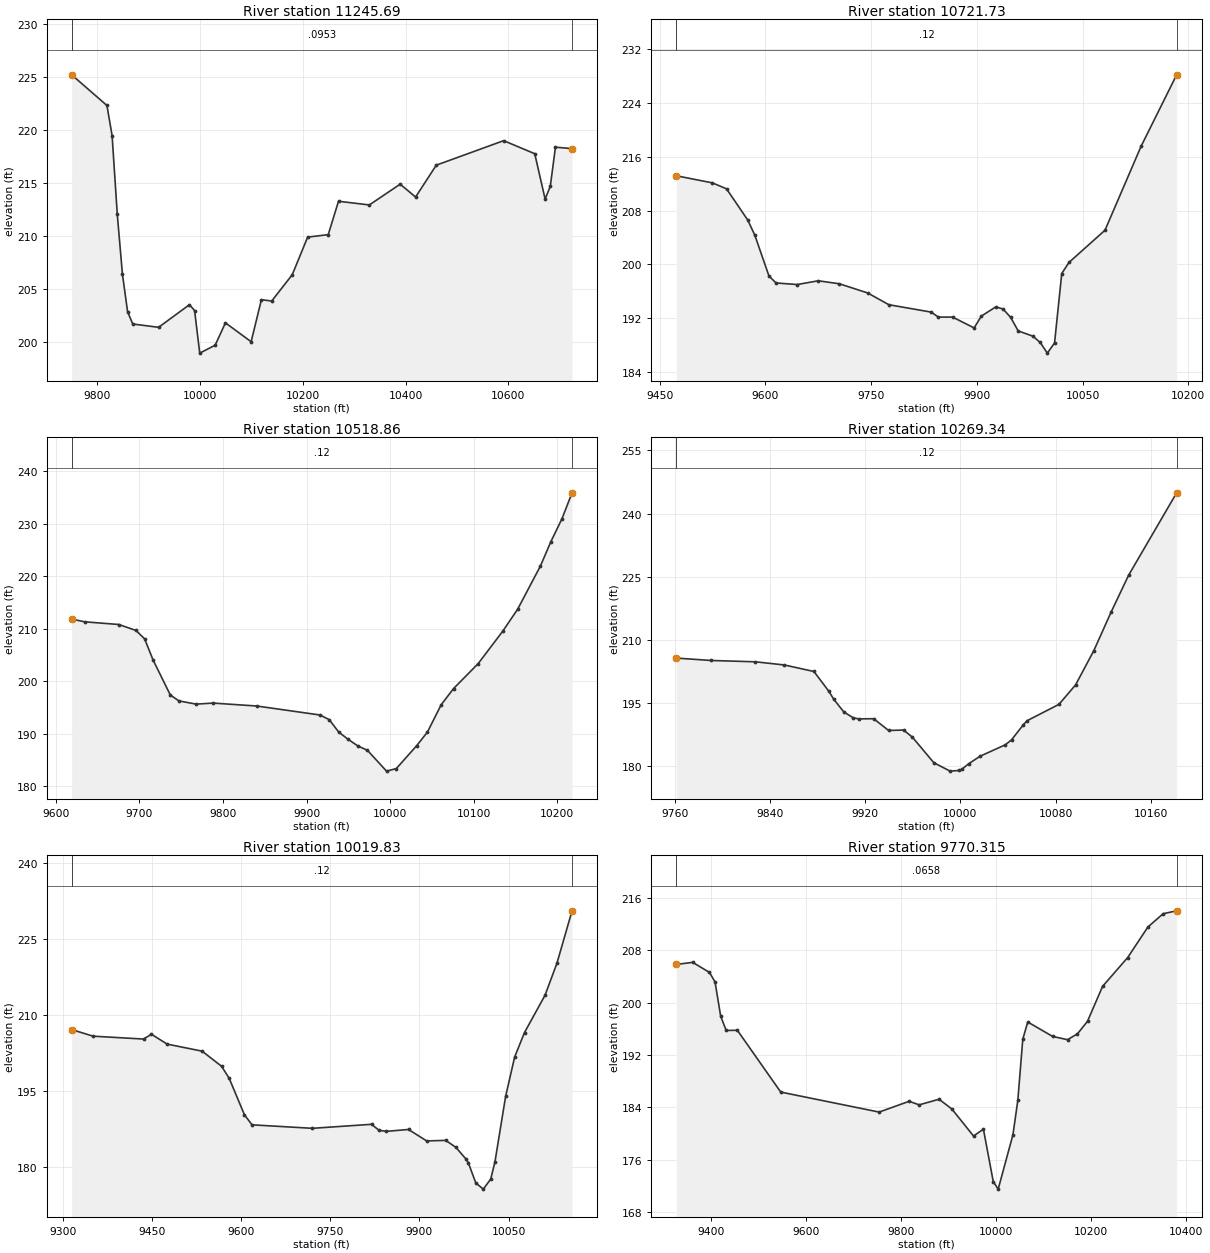
Type RM Length L Ch R = 1 ,11245.69,523.958000,523.958000,523.958000
XS GIS Cut Line= 5
772303.269614458714992.539142236772127.922392249714975.178031132
772028.964058906714971.705808908771631.394614458714969.969697803
771332.996925473715008.098291412
#Sta/Elev= 30
9750.244225.17989818.848 222.2939828.897219.45939838.946212.05429848.995206.4118
9859.043202.87349869.092201.72259919.337201.40999979.404203.5384 9989.41202.9891
9999.416198.980610029.43199.726310049.43201.832210099.43200.055110119.43 204.011
10139.43203.883910179.43206.361310209.43209.903210249.43210.132610269.43213.2771
10329.44212.931110389.44214.885210419.44213.674210459.73216.675610590.79218.9817
10651.28217.753510671.44213.489510681.52214.6727 10691.6218.368110723.87218.2325
#Mann= 3 , 0 , 0
9750.244  0.0953       09750.244  0.0953       010723.87  0.0953       0
#XS Ineff= 2 , 0
       0                               0
Bank Sta=9750.244,10723.87
Exp/Cntr=0.3,0.1

Type RM Length L Ch R = 1 ,10721.73,202.876000,202.876000,202.876000
XS GIS Cut Line= 6
772285.664035906714657.817076934772182.820478229714644.860406387
 771921.02064452714632.967077901771880.747515554 714627.05395636
771795.023086697714602.348170012771585.663681045714557.192219767
#Sta/Elev= 30
9473.417213.16739524.695212.11359544.795211.22539574.945 206.5869584.962204.3297
9604.976198.29569614.983197.25919645.003197.02649675.024197.58369705.045197.1341
9745.073195.77569775.094194.03169835.243192.93399845.317192.19549865.532 192.196
9896.126190.58929906.406192.34469926.967193.71639937.298193.38529947.978192.1462
9958.658190.14299979.567189.36239989.797188.435910000.03186.847410010.26188.3601
10020.49198.663710030.72200.303210081.87 205.09110133.02 217.53110183.49228.1461
#Mann= 3 , 0 , 0
9473.417    0.12       09473.417    0.12       010183.49    0.12       0
#XS Ineff= 2 , 0
       0                               0
Bank Sta=9473.417,10183.49
Exp/Cntr=0.3,0.1

Type RM Length L Ch R = 1 ,10518.86,249.514300,249.514300,249.514300
XS GIS Cut Line= 6
772269.961063337714613.220634835772099.322477559714573.270761577
772037.342333343714553.988743582771974.950392402714526.761448381
771885.255350479714473.851225872771745.925042999 714350.13328091
#Sta/Elev= 30
9618.952211.82239634.318211.2981  9675.4 210.784 9695.94209.64469706.211208.0569
9716.481203.98599737.022 197.3579747.292196.23299767.833195.61929788.374 195.818
9840.623195.25739916.102193.55079927.165192.66759938.602190.28649950.041188.8908
9961.481187.6525 9972.92186.82629995.798182.858910007.48183.346310031.77187.6869
10044.64190.268310061.26195.5156   10076198.580810105.48203.338310134.96209.5262
10152.67 213.68110179.95221.916310192.53226.577810205.79230.935210217.82235.8622
#Mann= 3 , 0 , 0
9618.952    0.12       09618.952    0.12       010217.82    0.12       0
#XS Ineff= 2 , 0
       0                               0
Bank Sta=9618.952,10217.82
Exp/Cntr=0.3,0.1

Type RM Length L Ch R = 1 ,10269.34,249.514300,249.514300,249.514300
XS GIS Cut Line= 6
772249.782897327714431.672396983772169.045551512  714375.7561988
 772087.00003742714313.393775305772056.864262012 714288.88814581
772008.478933622714247.387464086771922.878854046714167.397676148
#Sta/Elev= 30
9760.892 205.6319790.175205.05989827.531204.74279851.859203.98989876.744202.4415
9889.305197.72169893.402 195.8449901.866192.81779909.928191.41529914.427191.1708
9926.988191.21719939.549188.41669952.109188.52219959.504186.8515 9977.62180.7488
9991.328178.7547    9999178.9149   10001179.158110006.97 180.51610016.63182.3134
10037.69185.003210042.98186.187110053.05189.823510056.15190.751210082.89194.6265
10096.88199.254510112.18 207.36810126.83216.589810141.47225.3073 10181.9244.9146
#Mann= 3 , 0 , 0
9760.892    0.12       09760.892    0.12       0 10181.9    0.12       0
#XS Ineff= 2 , 0
       0                               0
Bank Sta=9760.892,10181.9
Exp/Cntr=0.3,0.1

Type RM Length L Ch R = 1 ,10019.83,249.514300,249.514300,249.514300
XS GIS Cut Line= 6
772658.702078234714646.052395064772498.373656965714460.638847871
772411.650203948714351.783927071772280.324400787  714174.1258335
772176.816789409714038.769045327772139.162818865713984.083299477
#Sta/Elev= 30
  9314.8 207.0949350.817205.79199435.729205.2252 9449.01 206.1769475.478204.2282
9534.244202.84289567.135 199.855 9579.92197.47079605.492190.31139618.277188.3261
9719.974187.64079819.459188.43029831.894 187.252 9844.33187.04249881.636187.4122
9912.164185.15599944.231185.26199961.361183.89339977.682181.67689982.191180.8834
9994.845176.881610007.47175.659710019.99177.642710027.03180.985110045.05193.9227
10060.24201.679810076.84206.513810111.27213.830510131.43220.166510156.83230.4883
#Mann= 3 , 0 , 0
  9314.8    0.12       0  9314.8    0.12       010156.83    0.12       0
#XS Ineff= 2 , 0
       09829.245                       0
Bank Sta=9314.8,10156.83
Exp/Cntr=0.3,0.1

Type RM Length L Ch R = 1 ,9770.315,249.514300,249.514300,249.514300
XS GIS Cut Line= 6
772725.198821069714633.720242017772626.468428511714472.204807501
772549.624371023714306.138592072 772491.05237105714131.476296764
772413.089908886713857.168966045772342.270712208713658.504503424
#Sta/Elev= 30
9326.671205.85829361.258206.17919396.505204.64449408.254203.18429420.187197.9262
9431.752195.7611 9455.25195.78439546.513186.33269753.557 183.2719816.773184.9211
9837.744184.37599879.687185.23789906.481 183.7519952.264179.60479972.988180.6605
9993.712172.633110004.06171.482610035.11 179.79510045.46185.106610055.83 194.416
10066.29 197.05410118.57194.847810149.94194.347210170.88195.245710192.01197.1598
10223.71202.502410276.54206.911410319.03211.578810351.16213.623310379.54214.0633
#Mann= 3 , 0 , 0
9326.671  0.0658       09326.671  0.0658       010379.54  0.0658       0
#XS Ineff= 2 , 0
       0                               0
Bank Sta=9326.671,10379.54
Exp/Cntr=0.3,0.1

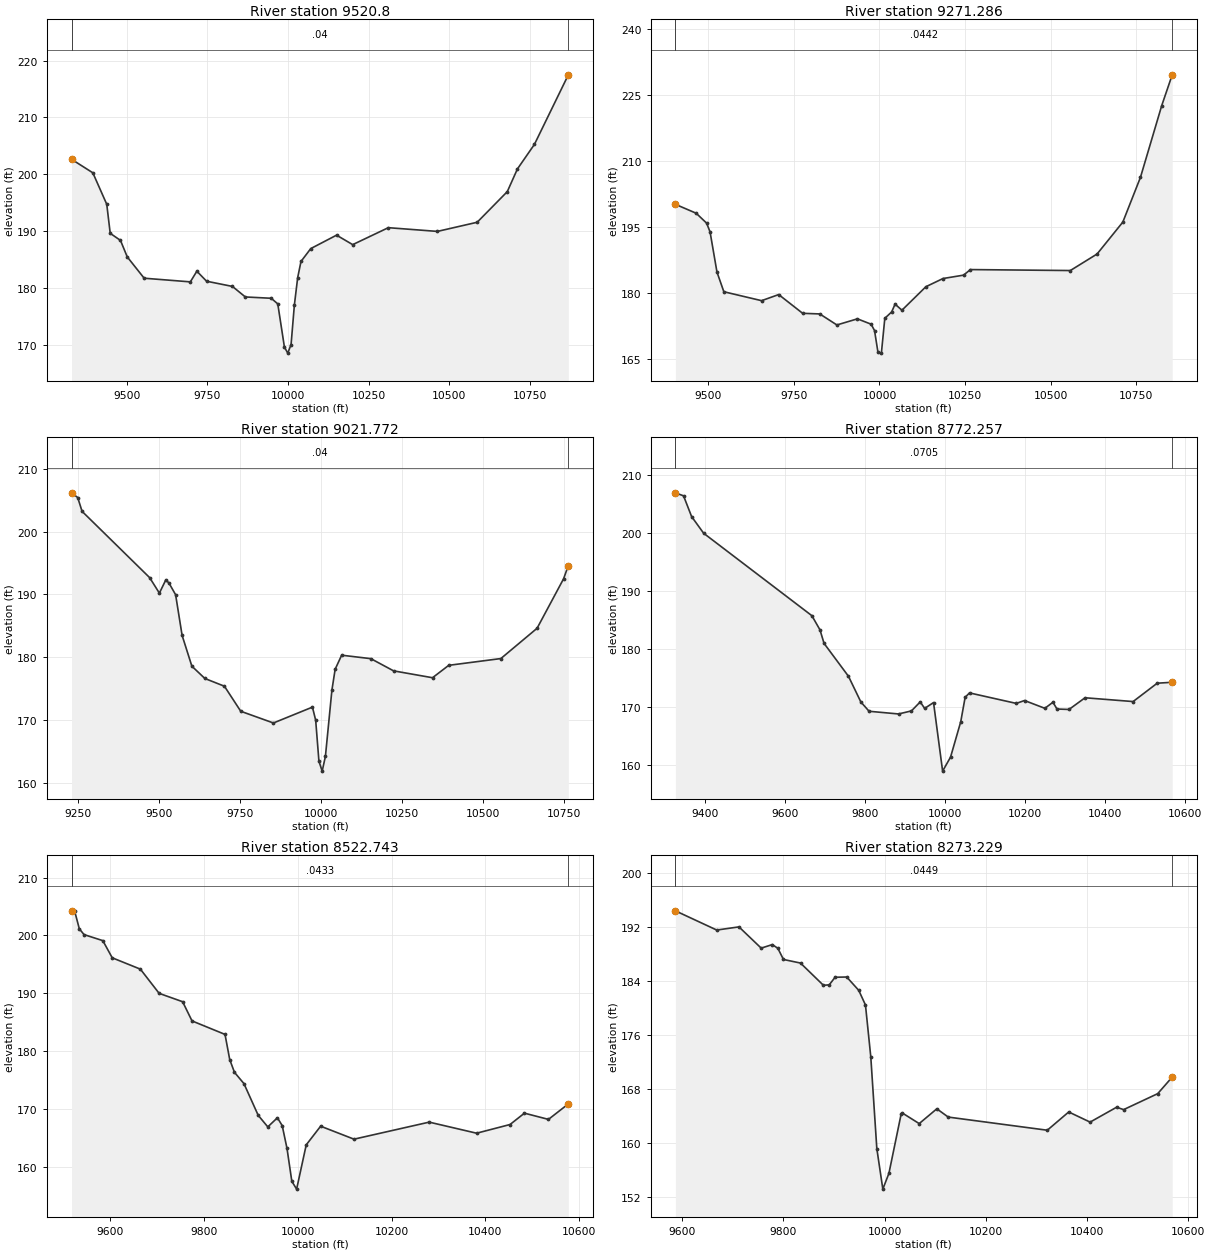
Type RM Length L Ch R = 1 ,  9520.8,249.514300,249.514300,249.514300
XS GIS Cut Line= 6
772807.473100232714625.260176121772724.898423016714409.001968223
772687.107890436714198.889406205772717.249950258713852.532317812
772691.660625583713590.642285015772561.463912766713125.825616205
#Sta/Elev= 30
9328.191202.63859394.393200.25479437.608194.71479448.326 189.6069480.217188.3567
9501.209185.45549553.688181.70539697.052181.06259717.213182.93899747.428181.1759
 9827.72180.25969867.724178.40689948.089 178.1769968.398177.18759989.047169.5734
9999.374168.522410009.65170.029610019.91176.985210030.17181.808210040.43184.6525
10070.74186.917410150.85189.282910200.93187.615210311.53190.598610463.81189.9426
10587.27191.551810680.75196.942310712.16200.930310764.99205.259810870.18217.4972
#Mann= 3 , 0 , 0
9328.191    0.04       09328.191    0.04       010870.18    0.04       0
#XS Ineff= 2 , 0
       0                               0
Bank Sta=9328.191,10870.18
Exp/Cntr=0.3,0.1

Type RM Length L Ch R = 1 ,9271.286,249.514300,249.514300,249.514300
XS GIS Cut Line= 6
 772978.00526063 714574.99963631772952.885566016714380.605177985
772940.718983863713760.558450325772927.458837469 713570.51410154
772892.478233729713348.208773592772837.277535164713135.794783278
#Sta/Elev= 30
9403.687200.0504 9464.52198.01939494.875195.77189504.993193.77629525.157184.6532
9545.234180.17979655.482178.14879705.513179.53819775.514175.27669825.514 175.134
9875.515  172.639935.516174.01949975.522 172.8039985.525171.35429995.528166.4314
10005.54 166.22610015.54 174.13710035.55175.592210045.55177.358710065.56175.9787
10135.58181.3225 10185.6183.184410245.66183.952310265.69185.216910557.59 184.998
10635.71188.756710710.94196.008310762.39206.163110824.68222.507610855.25229.4828
#Mann= 3 , 0 , 0
9403.687  0.0442       09403.687  0.0442       010855.25  0.0442       0
#XS Ineff= 2 , 0
       0                               0
Bank Sta=9403.687,10855.25
Exp/Cntr=0.3,0.1

Type RM Length L Ch R = 1 ,9021.772,249.514300,249.514300,249.514300
XS GIS Cut Line= 6
773191.350331396 714753.72779605773164.845824281714572.014840106
773162.472811619714426.754111251773197.293600362714048.756999606
 773197.58937494713607.688382447773144.649901466713230.728125194
#Sta/Elev= 30
9230.844206.14779249.938205.40359263.422203.20429471.719192.66919501.719190.2093
9521.719192.33829531.719191.76859551.719189.95629571.745 183.4919601.812178.5997
  9641.9176.6452 9702.18175.41369752.514171.43559853.183169.57249973.453172.0952
9983.457170.0049 9993.46163.502110003.47 161.92310013.47164.267610033.48174.7956
10043.49178.1172 10063.5180.345310153.53179.794610223.55177.856610343.58176.7646
10393.61178.736810554.25179.812210665.85184.624910747.51192.484210762.17194.5896
#Mann= 3 , 0 , 0
9230.844    0.04       09230.844    0.04       010762.17    0.04       0
#XS Ineff= 2 , 0
       0                               0
Bank Sta=9230.844,10762.17
Exp/Cntr=0.3,0.1

Type RM Length L Ch R = 1 ,8772.257,249.514300,249.514300,249.514300
XS GIS Cut Line= 6
773326.353395538714715.205646095773315.238721162714524.546595478
 773342.53897113714291.352909211773470.531876931713971.976075384
773513.118926229713800.590068674773501.036110524713507.951706481
#Sta/Elev= 30
9324.884206.85939345.269 206.3429365.399202.77329395.506199.9015 9666.19185.7018
 9686.49183.25589696.654180.93329757.729175.26569788.655170.84989809.273169.2402
9882.952168.7775  9915.2169.30439937.168170.85369948.221169.7347 9970.46170.7399
9993.175158.932710013.02161.351110038.49167.437310049.52171.650810060.45172.4041
10177.37170.595410198.01171.091710248.83169.7503 10269.1170.794510279.18169.6282
10309.27169.553310349.34 171.56610469.55170.913210529.88174.077310567.36174.2299
#Mann= 3 , 0 , 0
9324.884  0.0705       09324.884  0.0705       010567.36  0.0705       0
#XS Ineff= 2 , 0
       0                10073.04       0
Bank Sta=9324.884,10567.36
Exp/Cntr=0.3,0.1

Type RM Length L Ch R = 1 ,8522.743,249.514300,249.514300,249.514300
XS GIS Cut Line= 6
773634.852735573714611.599879871773633.618838593714320.485212896
773683.457053516714054.693600647773692.780101968713929.378312808
773676.465218244713772.306780454773632.266417154713563.841238584
#Sta/Elev= 30
9517.759204.24359524.377204.22469534.404201.13799544.432200.13319584.541 199.086
9604.582196.11729664.601194.15429704.613189.96599754.642188.52219774.697185.1993
9845.041182.86779855.111178.50359865.181 176.311 9885.44174.34929915.844168.8631
9936.263166.86969956.746168.44289966.988 167.089 9977.23163.13219987.472157.4599
9997.714 156.10210018.21163.762610048.92166.988510120.05164.742410280.39167.6914
10381.44165.775210452.71167.2784 10483.4169.241510534.63168.165710576.99170.8439
#Mann= 3 , 0 , 0
9517.759  0.0433       09517.759  0.0433       010576.99  0.0433       0
#XS Ineff= 2 , 0
       0                10083.65       0
Bank Sta=9517.759,10576.99
Exp/Cntr=0.3,0.1

Type RM Length L Ch R = 1 ,8273.229,249.514200,249.514200,249.514200
XS GIS Cut Line= 6
774091.174366181714480.150996136773977.522643734714232.310613886
773852.241875163714030.885624642773804.092920626713932.843644481
773737.267182132713753.435224536773686.506175425713590.025949477
#Sta/Elev= 30
9586.486194.33599668.195191.49069712.132 191.958 9756.07188.81229778.039189.3394
9789.023188.78569800.063187.13369833.755186.60279879.122183.30589890.609183.3811
9902.096 184.502 9925.09184.53699948.888182.56139962.155180.39459972.687172.7032
9984.586159.14529996.486153.131610008.51155.468810032.62164.223810034.85164.4094
10068.37162.834510103.19165.023710125.76163.798810321.54161.852110363.89164.5555
10406.15163.0538 10458.5165.258210472.38164.903210539.79167.267810568.43169.7223
#Mann= 3 , 0 , 0
9586.486  0.0449       09586.486  0.0449       010568.43  0.0449       0
#XS Ineff= 2 , 0
       0                10099.98       0
Bank Sta=9586.486,10568.43
Exp/Cntr=0.3,0.1

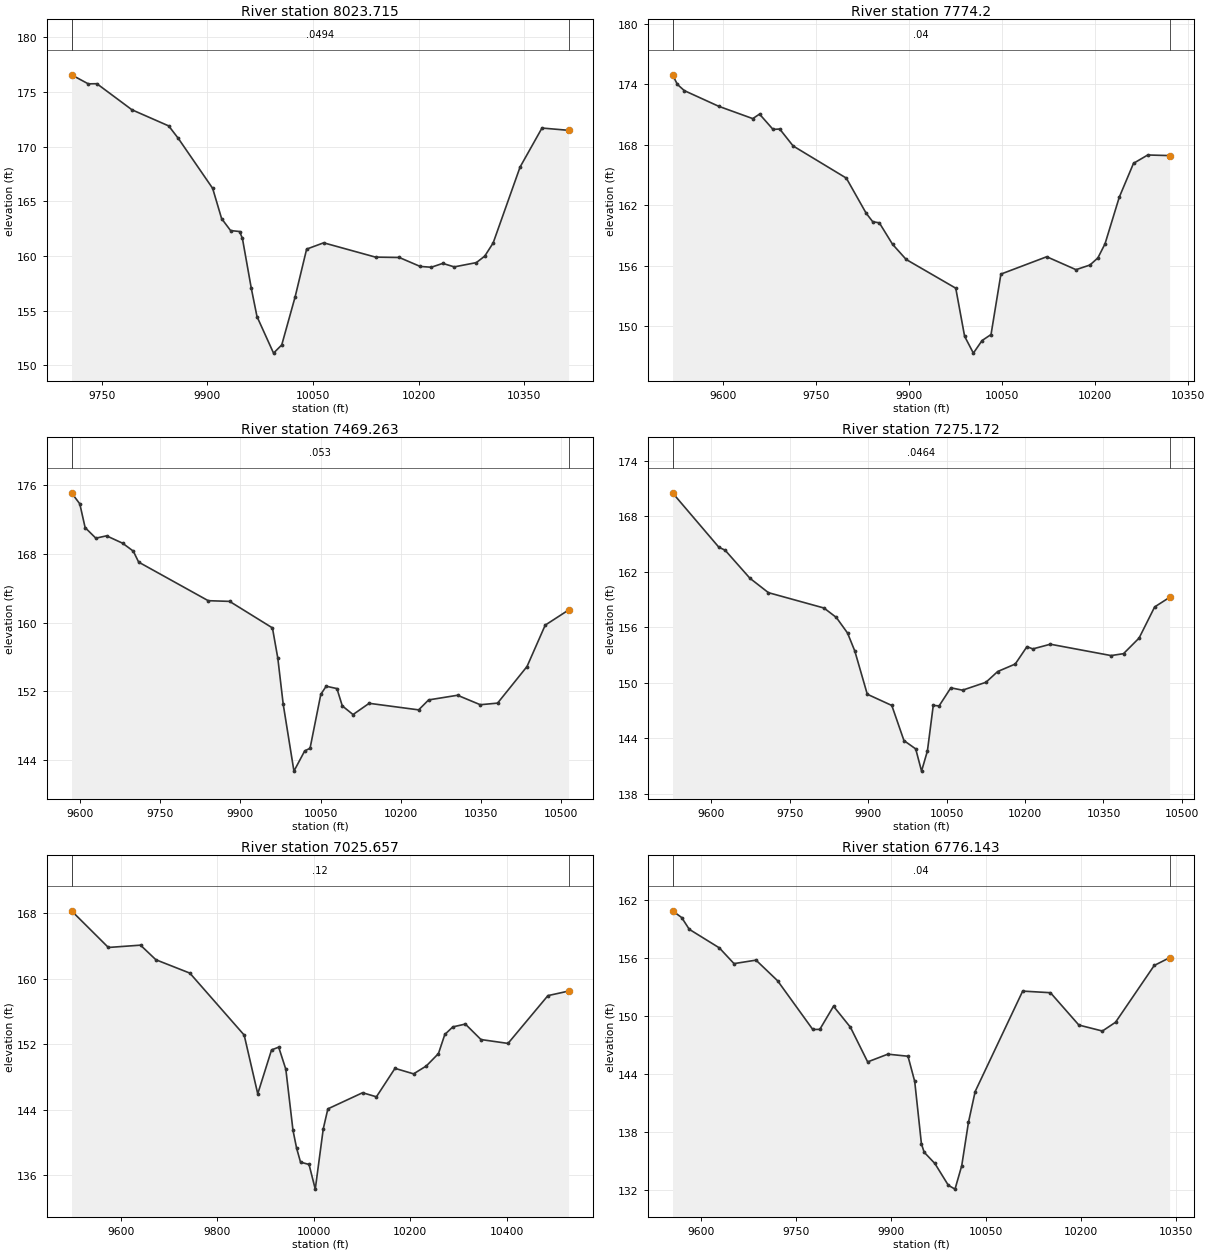
Type RM Length L Ch R = 1 ,8023.715,249.514300,249.514300,249.514300
XS GIS Cut Line= 6
   774272.101654714135.096579659774199.246052391714035.735180581
774148.034024591713983.523183461773982.665994103 713867.02171793
773912.399928306713796.420375513773803.103440336713621.342196686
#Sta/Elev= 30
9706.995 176.5619730.801175.73479742.981175.74829792.772173.36349844.967171.8882
 9858.61170.74529907.354166.17759920.081163.40899932.807162.31639945.534162.2309
9949.609 161.599 9962.17157.04989970.305154.44999993.791151.106210005.44151.8565
10024.51156.268310040.76160.620110064.96161.195610138.59159.886810172.34159.8531
10201.95159.035810217.78158.961910233.98159.314210250.36158.994210281.71159.3857
10293.64159.979910305.57161.1835 10343.8168.128810374.88171.6938 10412.7171.4851
#Mann= 3 , 0 , 0
9706.995  0.0494       09706.995  0.0494       0 10412.7  0.0494       0
#XS Ineff= 2 , 0
       0                10076.12       0
Bank Sta=9706.995,10412.7
Exp/Cntr=0.3,0.1

Type RM Length L Ch R = 1 ,  7774.2,304.936800,304.936800,304.936800
XS GIS Cut Line= 6
774453.676098466714192.125822116774390.141656779714056.221217175
774297.034507682713822.215631388 774271.63363985713784.583990619
774200.488018687713707.113752714774071.216484753713494.317665685
#Sta/Elev= 30
9518.086 174.9199526.008173.96559537.125 173.3539592.597171.79889647.501170.5766
9658.482 171.0229680.239 169.5059691.039169.54349712.637167.8637 9798.48164.6715
9830.435 161.1939841.086160.34579851.738160.23659873.077158.10559895.044   156.6
9975.001153.75279989.276 148.98310003.41  147.3110017.47148.560710031.91149.1551
10047.84155.150610121.75156.871910169.01155.588310191.45156.051510204.23156.7518
10215.81158.158310238.79162.781710261.76166.139910284.73166.967410319.97166.9068
#Mann= 3 , 0 , 0
9518.086    0.04       09518.086    0.04       010319.97    0.04       0
#XS Ineff= 2 , 0
       0                 10111.2       0
Bank Sta=9518.086,10319.97
Exp/Cntr=0.3,0.1

Type RM Length L Ch R = 1 ,7469.263,194.091800,194.091800,194.091800
XS GIS Cut Line= 6
774534.302741163714200.447051381774520.674128324713833.988795012
774501.576906115713639.544350579774458.505279749713473.949905925
774412.477510146713365.443632625774375.427542662713296.480820355
#Sta/Elev= 30
 9584.27175.06189599.727173.78359609.734171.02149629.748169.79659649.762170.0692
9679.783169.21359699.796168.29329709.803167.01899839.893162.53979879.921162.4589
9960.013159.37849970.061155.85929980.109150.534210000.21142.7523 10020.3145.0957
10030.35145.408610050.45151.666710060.49152.609710080.59152.337910090.64150.3258
10110.73149.320110140.88150.624910233.42149.863810252.09  151.0210306.11151.5605
10348.67150.461510381.05150.648710436.08154.898510470.11159.701810513.87  161.46
#Mann= 3 , 0 , 0
 9584.27   0.053       0 9584.27   0.053       010513.87   0.053       0
#XS Ineff= 2 , 0
       0                10220.75       0
Bank Sta=9584.27,10513.87
Exp/Cntr=0.3,0.1

Type RM Length L Ch R = 1 ,7275.172,249.514300,249.514300,249.514300
XS GIS Cut Line= 6
774914.406871396714069.139027549774843.901934423713961.425219011
774681.329482944 713700.78332544774552.477965538713444.724853986
774511.942066246713373.406368983774432.386374458713251.555544571
#Sta/Elev= 30
9526.254  170.539614.863 164.6499626.815164.32839674.349161.28859709.602159.7379
9815.779158.0785 9839.35157.06039860.765155.37969874.708153.42879898.556148.7587
9945.422147.54529968.667143.74659991.108142.849510002.27140.446510013.47142.6212
10024.66147.547510035.85147.501210058.24149.451410080.63149.1975 10125.4150.0525
10147.78151.212910181.36152.023310203.75153.902410214.94153.657410248.52154.1649
10364.57152.9376 10388.3153.143410418.07154.829910447.85158.197610476.41159.2298
#Mann= 3 , 0 , 0
9526.254  0.0464       09526.254  0.0464       010476.41  0.0464       0
#XS Ineff= 2 , 0
       0                10174.53       0
Bank Sta=9526.254,10476.41
Exp/Cntr=0.3,0.1

Type RM Length L Ch R = 1 ,7025.657,249.514300,249.514300,249.514300
XS GIS Cut Line= 6
775238.578871571 713916.34727863774951.127052401713630.196484672
774855.669896654713519.330171573774685.990019557713376.388297642
774625.279594178713319.189017891 774506.45774412713193.133055821
#Sta/Elev= 30
9498.057168.28869574.453163.81199641.086164.09519672.989162.31149743.372160.6795
9855.984153.11279884.138145.93769912.741151.29929927.553151.63359942.366148.9284
9957.178141.48399964.686139.29779972.832137.58629990.472137.306110003.38134.2924
   10020141.667810029.53144.098210101.51146.068110130.16145.569110168.67149.0461
10207.22148.373810233.63149.338910258.77150.849410271.95153.183510288.56154.1094
10314.53154.455810346.89152.5643   10403152.091810485.69157.928910528.62 158.487
#Mann= 3 , 0 , 0
9498.057    0.12       09498.057    0.12       010528.62    0.12       0
#XS Ineff= 2 , 0
       0                               0
Bank Sta=9498.057,10528.62
Exp/Cntr=0.3,0.1

Type RM Length L Ch R = 1 ,6776.143,249.514300,249.514300,249.514300
XS GIS Cut Line= 6
775347.201538963713517.561429955775240.338497798713451.300237605
775142.318668308713401.996015435774788.286062294713265.703457614
774698.930291524713213.901479481  774645.4422861713174.581957557
#Sta/Elev= 30
9555.184160.83429569.709160.13799581.613 158.9299629.073157.01179652.303155.3863
9687.007155.74629721.059153.62069776.656148.58889787.731148.60039809.372150.9908
9836.177148.80999863.279145.2428 9895.12146.04169926.953145.82779937.564143.2313
9948.175136.78099952.538135.91719969.397134.75979990.618132.512910001.19132.1136
 10011.8  134.5310022.41 139.00310033.01142.186310108.03152.550210151.87152.3838
10196.74149.044910233.88148.429410254.63149.334510315.71155.195310339.98155.9973
#Mann= 3 , 0 , 0
9555.184    0.04       09555.184    0.04       010339.98    0.04       0
#XS Ineff= 2 , 0
       0                               0
Bank Sta=9555.184,10339.98
Exp/Cntr=0.3,0.1