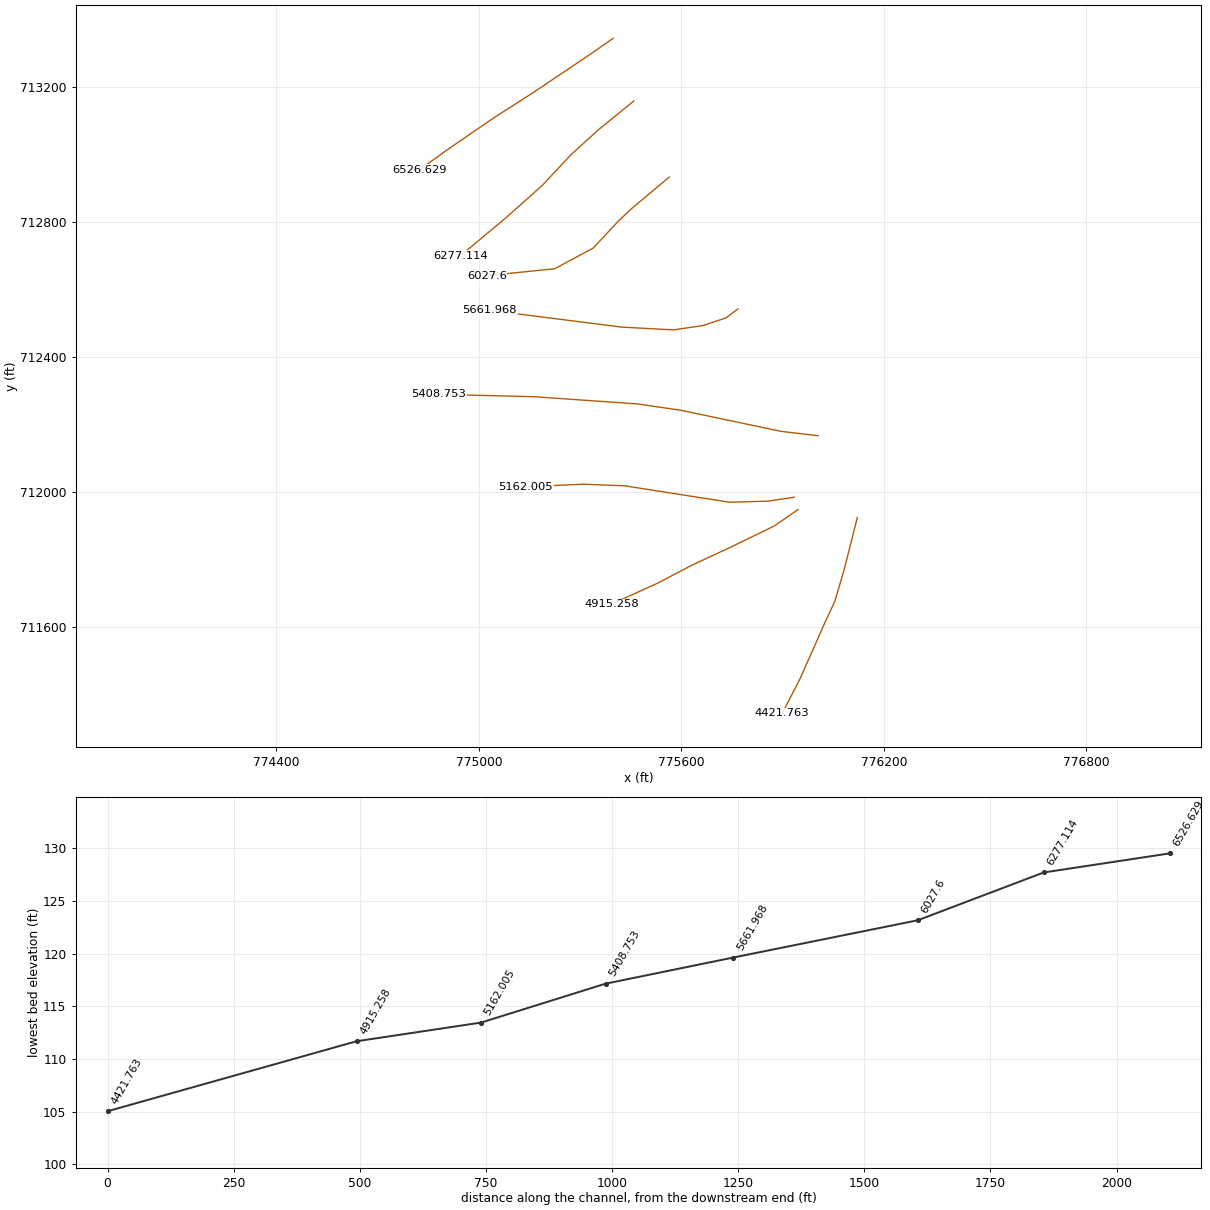
HEC-RAS study 6602_ras.prj: 6602

--- 6602_ras.g01 (geometry) --- (continued)

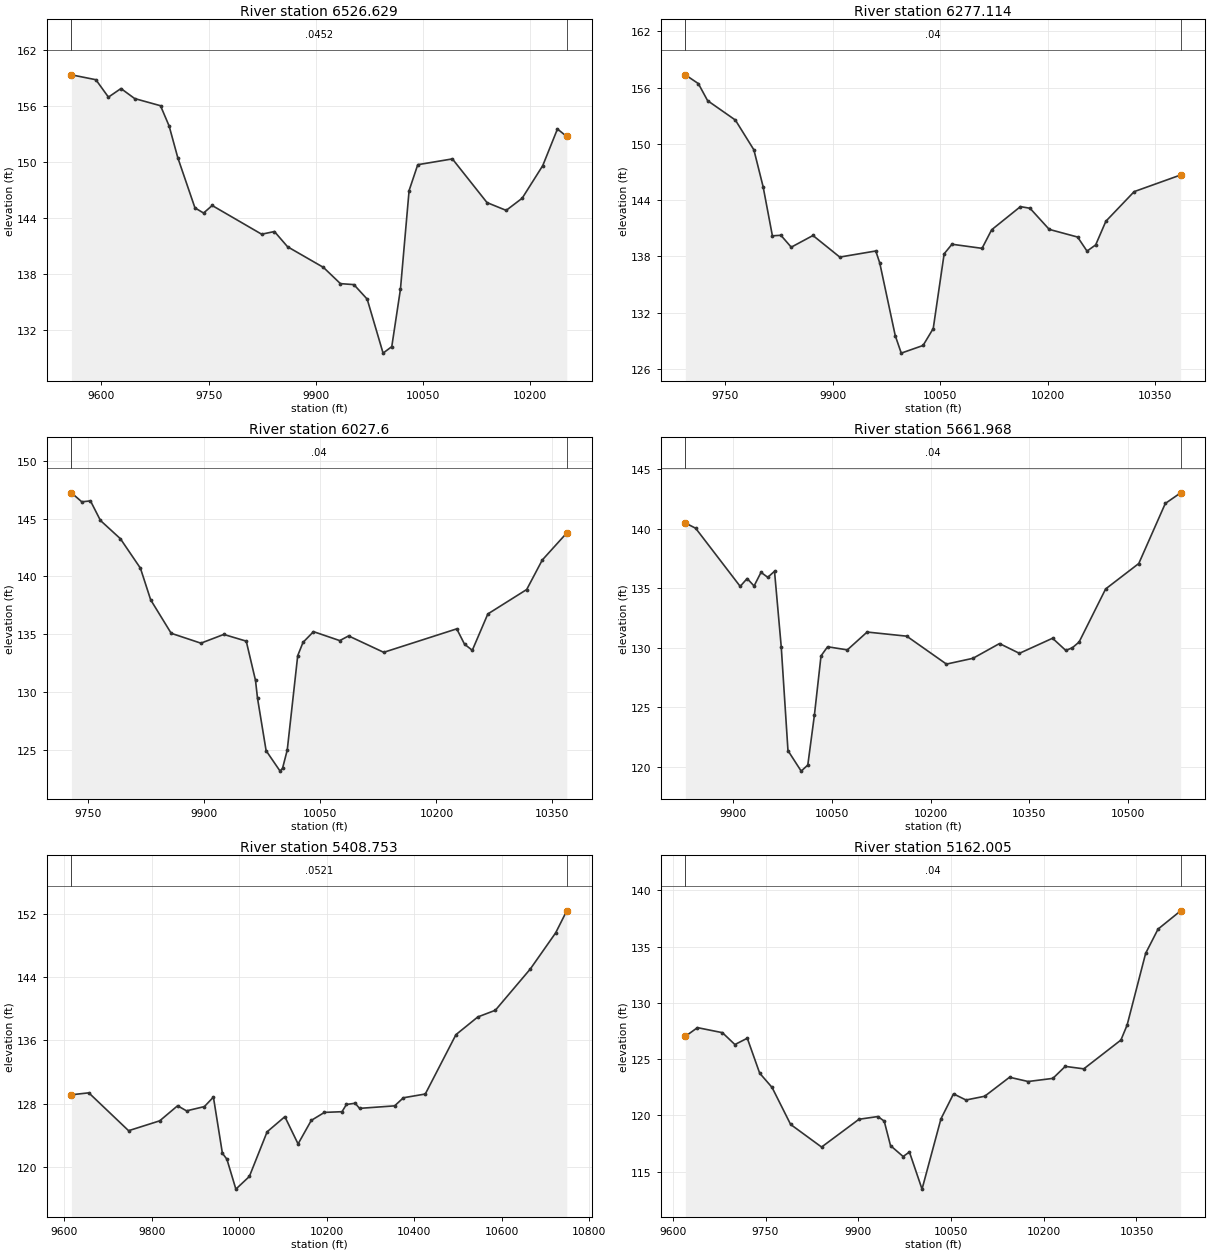
Type RM Length L Ch R = 1 ,6526.629,249.514300,249.514300,249.514300
XS GIS Cut Line= 6
775397.713138691713344.498850996775324.706337034713293.859291774
775158.398438862713182.105975287 775046.52208928713110.566327548
774904.442330547713013.229096904774824.448076572712955.295620689
#Sta/Elev= 30
9558.084159.38359592.296 158.8589609.841  156.999627.387157.91249646.577156.8354
9682.724156.06719694.772153.8922 9706.82150.50829730.916145.10349742.964144.5519
9755.012145.36019824.183142.27979842.113142.56469860.492140.93229910.684138.7168
9934.423136.97569953.303136.86929971.866135.31349994.104 129.51710006.28130.2144
 10018.4136.369710030.51146.964410042.62149.738110091.08150.360610139.53145.6719
10166.35144.836710188.67146.1378 10217.5 149.63910238.06153.568610251.09152.7653
#Mann= 3 , 0 , 0
9558.084  0.0452       09558.084  0.0452       010251.09  0.0452       0
#XS Ineff= 2 , 0
       0                               0
Bank Sta=9558.084,10251.09
Exp/Cntr=0.3,0.1

Type RM Length L Ch R = 1 ,6277.114,249.514300,249.514300,249.514300
XS GIS Cut Line= 6
775459.212129974713159.135136122 775352.45661837713072.249709505
775272.327545719712999.104784189775186.343180215712907.362170827
775079.466401212712812.264346463774944.402028084 712699.57413954
#Sta/Elev= 30
9694.306157.35579712.467156.42139725.378154.60339764.112152.53719789.934149.3626
9802.846145.42439815.757140.20349827.604140.26029842.048138.99319872.371140.2379
9909.748137.93859959.956138.58759965.525137.3076 9987.12129.57089995.502127.7047
10025.91128.520210040.13130.327910055.34138.287210066.26139.305610108.21138.8686
 10121.6140.847310161.75143.313910175.11143.138310201.91 140.88910241.49140.0724
10254.64138.5755 10266.7139.235210280.94141.756410320.39144.911110385.24146.6857
#Mann= 3 , 0 , 0
9694.306    0.04       09694.306    0.04       010385.24    0.04       0
#XS Ineff= 2 , 0
       0                10085.64       0
Bank Sta=9694.306,10385.24
Exp/Cntr=0.3,0.1

Type RM Length L Ch R = 1 ,  6027.6,365.631700,365.631700,365.631700
XS GIS Cut Line= 6
775564.073823661712933.469180644775453.664408416712840.999376968
775413.390890211712803.262057662775338.758888602712723.089436665
775224.294991016712661.618084222 775023.46025336712641.280389276
#Sta/Elev= 30
9727.993147.22259741.386146.44449752.615146.52559765.524144.83179791.341143.2533
9817.213140.70839830.474137.97229856.996135.08129895.427134.22619925.014134.9822
9954.054134.40179966.028131.01059968.646129.45919979.759124.9338 9997.83123.1663
   10001123.410410007.09124.992210020.63133.1516 10027.5134.296710041.02135.2232
10074.99134.448610086.43134.854110131.83133.435610226.28 135.46510236.33134.1401
10246.38133.610310266.48136.752210316.74138.864310336.84141.411110368.54 143.752
#Mann= 3 , 0 , 0
9727.993    0.04       09727.993    0.04       010368.54    0.04       0
#XS Ineff= 2 , 0
       0                10055.53       0
Bank Sta=9727.993,10368.54
Exp/Cntr=0.3,0.1

Type RM Length L Ch R = 1 ,5661.968,253.215800,253.215800,253.215800
XS GIS Cut Line= 6
775767.557737052712542.728454709775731.665079355712515.876258552
775663.474473864712493.349975079775576.519734591712480.509997129
  775422.6966196 712488.80341588775031.880653739712538.388176933
#Sta/Elev= 30
9827.001140.48869842.684140.04749910.384135.15859920.936135.81999931.485135.1921
9942.035136.33889952.315135.91939962.546136.43019972.778130.07329983.009121.3535
 10003.1119.628110013.14120.141910023.19124.339610033.22129.315810043.22130.0828
10073.22129.8206 10103.3131.320310163.48130.973810223.85128.625710264.17129.1129
10304.49130.352410334.73129.530910385.13130.798610405.29129.771310415.37130.0059
10425.45130.480810465.77 134.94210516.17137.081710556.49142.1297 10579.8143.0235
#Mann= 3 , 0 , 0
9827.001    0.04       09827.001    0.04       0 10579.8    0.04       0
#XS Ineff= 2 , 0
       0                10124.78       0
Bank Sta=9827.001,10579.8
Exp/Cntr=0.3,0.1

Type RM Length L Ch R = 1 ,5408.753,246.747400,246.747400,246.747400
XS GIS Cut Line= 6
776004.565337513712166.885072356 775895.26012813712179.800963395
775599.504963098712242.101351663775469.964366962712261.083958768
775163.976729752712282.377604897774881.782723659712289.614023562
#Sta/Elev= 30
9616.271129.11399656.006129.35869746.956124.55629818.121125.80869859.004127.7202
9879.445127.0714 9920.33127.61639940.872128.82049961.414121.69399971.685120.9444
9992.228117.143210023.04118.7493 10063.7124.416110104.22126.332610134.43122.8777
10164.63125.863510194.75126.877110234.91126.965210244.94127.882210264.97128.0366
10274.99 127.38810355.15127.706510375.19128.731910425.29129.209110495.39136.7403
10545.43 138.98810585.46139.833110665.48145.076310723.33149.651710748.71152.4475
#Mann= 3 , 0 , 0
9616.271  0.0521       09616.271  0.0521       010748.71  0.0521       0
#XS Ineff= 2 , 0
       09916.607                       0
Bank Sta=9616.271,10748.71
Exp/Cntr=0.3,0.1

Type RM Length L Ch R = 1 ,5162.005,246.747400,246.747400,246.747400
XS GIS Cut Line= 6
775934.295714204711984.605903362775856.340990146711972.943922519
   775742.795505711969.815205408775431.470710509712018.475433148
775308.768542759712023.179583753775138.528849621712015.802397726
#Sta/Elev= 30
9620.305127.0196 9639.93127.7953 9680.31127.34699700.491126.29279720.536 126.854
9740.582123.74879760.607122.48199790.607119.19729840.694 117.1869901.194119.6557
9931.793119.89769941.992119.49269952.192117.31419972.591116.34649982.791116.7466
10003.18113.449210033.76119.690910054.09121.911410074.25121.3661 10104.5121.6988
10144.73123.388410174.79123.009310214.81123.287110234.81124.352910264.82124.1339
10324.85126.691110334.86128.018710364.87 134.396 10384.9136.547910421.48138.1711
#Mann= 3 , 0 , 0
9620.305    0.04       09620.305    0.04       010421.48    0.04       0
#XS Ineff= 2 , 0
       09847.635                       0
Bank Sta=9620.305,10421.48
Exp/Cntr=0.3,0.1

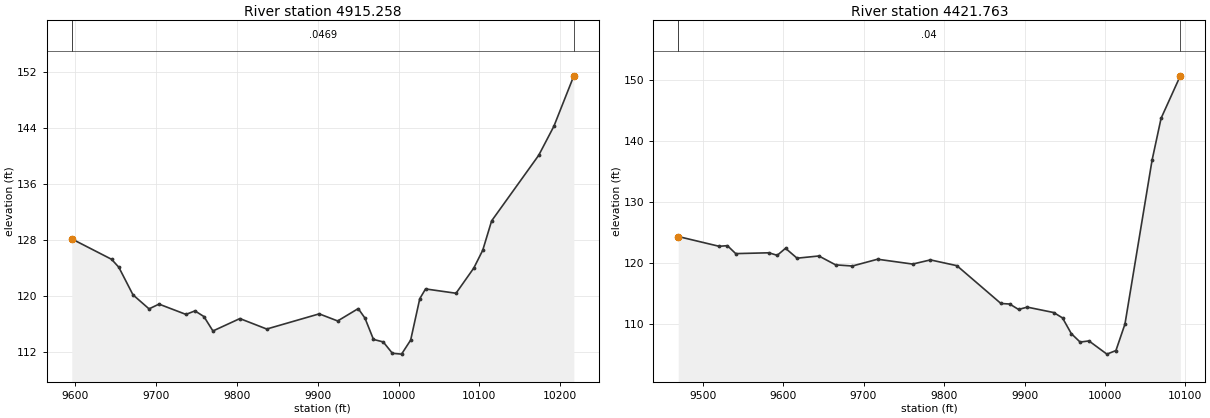
Type RM Length L Ch R = 1 ,4915.258,493.494800,493.494800,493.494800
XS GIS Cut Line= 6
775945.509125948711948.110399157          775875711899.326861501
775741.434256822711834.401875347775632.348093599711783.860187292
775532.435019284711731.423687026775392.283073902711667.587512374
#Sta/Elev= 30
 9595.47128.1636 9644.73125.24529653.664 124.1149671.239120.15959691.107118.1527
9703.448118.83229736.804117.35929747.923117.86439759.042117.05019770.161114.9893
9803.517116.76369836.756115.26749901.711117.43729924.537116.42349949.966118.1907
9958.289116.83659968.832113.78089980.942113.42059992.269111.7951 10003.6111.6766
10014.86 113.68310026.13119.6037 10033.3121.0055   10071 120.38710093.03123.9995
10104.05126.537210115.07130.743310173.39140.138110192.14144.288310216.82151.4977
#Mann= 3 , 0 , 0
 9595.47  0.0469       0 9595.47  0.0469       010216.82  0.0469       0
#XS Ineff= 2 , 0
       09830.829                       0
Bank Sta=9595.47,10216.82
Exp/Cntr=0.3,0.1

Type RM Length L Ch R = 1 ,4421.763,0.000000,0.000000,0.000000
XS GIS Cut Line= 6
776121.290375978711924.238871381776082.227875948711770.159010261
776054.792790502711676.379238591776026.024828285711614.986392766
775952.428441584711448.580561131775898.746981919711344.078634173
#Sta/Elev= 30
9469.706124.34559520.503122.74049530.819122.84359541.136 121.5389582.401121.6732
9592.717121.25759603.034122.4121 9617.38120.78629644.455121.15069665.293119.6905
9686.132119.50359717.389120.61639761.025119.81999783.111120.50659816.024119.5542
9870.696113.3483 9881.63113.25879892.564 112.3729903.499112.74799936.302 111.861
9947.236110.9792 9958.17108.39679969.105107.01159980.109107.198810002.39105.0308
10013.61105.618410024.84109.970110058.52136.880310069.75143.772310093.62150.7366
#Mann= 3 , 0 , 0
9469.706    0.04       09469.706    0.04       010093.62    0.04       0
#XS Ineff= 2 , 0
       0                               0
Bank Sta=9469.706,10093.62
Exp/Cntr=0.3,0.1